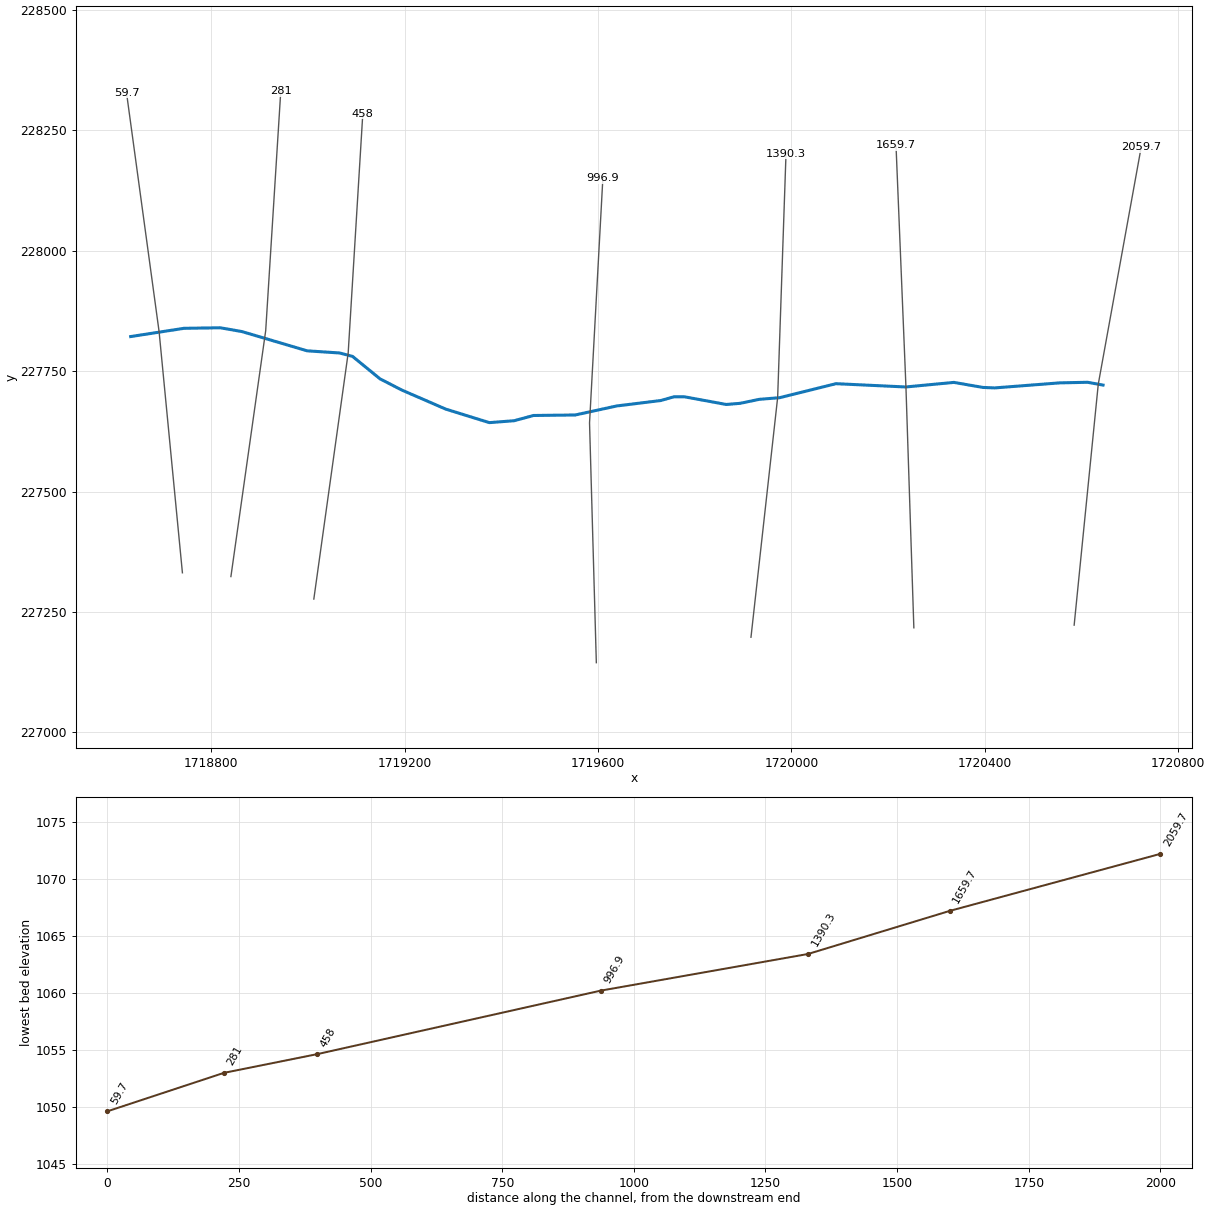
--- McKnyRnTr.prj (project) ---

Proj Title=McKnyRnTr
Current Plan=p01
Geom File=g01
Flow File=f01
Plan File=p01
DSS Export Rating Curves=0
DSS Export Rating Curve Sorted=0
DSS Export Volume Flow Curves=0
DXF OffsetX=0
DXF OffsetY=0
DXF ScaleX=0
DXF ScaleY=0

--- McKnyRnTr.p01 (plan) ---

Plan Title=Floodplain
Program Version=4.00
Geom File=g01
Flow File=f01
K Sum by GR=0
Std Step Tol=0.01
Critical Tol=0.01
Num of Std Step Trials=20
Max Error Tol=0.3
Flow Tol Ratio=0.001
Split Flow NTrial=30
Split Flow Tol=0.02
Split Flow Ratio=0.02
Log Output Level=0
Friction Slope Method=1
Unsteady Friction Slope Method=2
Unsteady Bridges Friction Slope Method=1
Global Log Level=0
CheckData=False
Run HTab=0
Run UNet=0
Run PostProcess=0
UNET Theta=0
UNET Theta Warmup=0
UNET ZTol=0
UNET ZSATol=0
UNET MxIter=0
UNET MaxInSteps=0
UNET DtIC=0
UNET DtMin=0
UNET MaxCRTS=0
UNET WFStab=0
UNET SFStab=0
UNET WFX=0
UNET SFX=0
UNET DSS MLevel=0
UNET DZMax Abort=0
UNET Convert EG Bridges=0
UNET Use Existing IB Tables=0
UNET Froude Limit=0
UNET Froude Power=0
Write IC File=0
Echo Input=False
Echo Output=False
Write Detailed=0

--- McKnyRnTr.f01 (steady flow) ---

Flow Title=NFF Regression Equation
Program Version=4.00
Number of Profiles=1
Profile Names=P100yr
River Rch & RM=McKnyRnTr,Main      ,2059.7
739.0180
River Rch & RM=McKnyRnTr,Main      ,458
800.5936
River Rch & RM=McKnyRnTr,Main      ,281
866.6811
River Rch & RM=McKnyRnTr,Main      ,59.7
874.2293
Boundary for River Rch & Prof#=McKnyRnTr,Main      ,1
Up Type=0
Dn Type=3
Dn Slope=0.010175

--- McKnyRnTr.g01 (geometry) ---

Geom Title=USGS 3m DEM
Program Version=4.00

River Reach=McKnyRnTr     ,Main
Reach XY= 30
     1720644.514      227720.865     1720612.537      227726.636
     1720555.132      227725.433     1720420.197      227714.947
     1720396.201      227715.958     1720336.115      227726.385
     1720236.480      227716.916     1720092.234      227723.724
     1719975.817      227694.719     1719933.145      227691.200
     1719894.332      227683.006     1719865.315      227680.601
     1719778.526      227696.591     1719757.210      227696.602
     1719729.925      227688.811     1719638.659      227677.505
     1719552.974      227658.793     1719466.661      227657.754
     1719426.906      227646.929     1719375.369      227642.899
     1719285.288      227670.930     1719194.293      227710.508
     1719149.240      227733.754     1719092.357      227780.381
     1719065.598      227787.458     1718998.509      227791.904
     1718863.272      227831.973     1718818.755      227839.738
     1718743.751      227838.628     1718633.512      227821.503

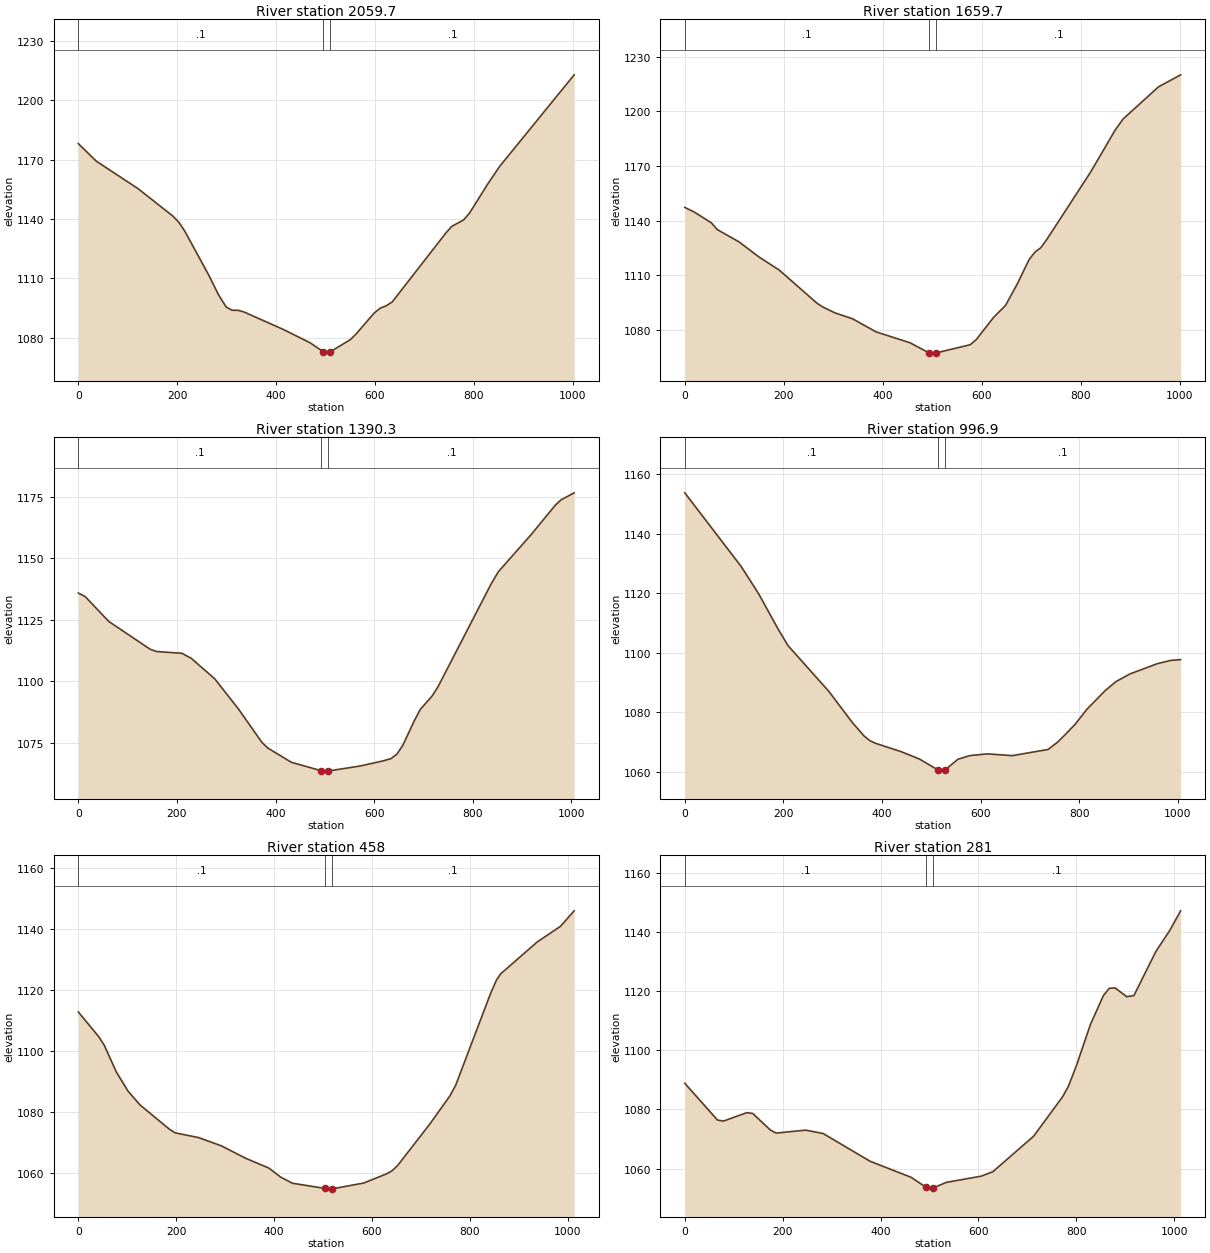
Type RM Length L Ch R = 1 ,2059.7,397.013,400,404.958
XS GIS Cut Line= 3
     1720584.802      227222.714     1720634.673      227722.641
     1720723.514      228214.851
#Sta/Elev= 30
       0 1178.16    36.5 1169.25   120.1 1155.52   191.6 1141.44   203.6 1138.29
   215.5 1133.80   265.1 1111.03   283.4 1101.75   299.0 1095.55   311.0 1093.91
   322.9 1093.89   334.8 1093.06   413.6 1084.30   467.9 1077.57   494.9 1073.04
   501.9 1072.23   509.9 1072.95   550.1 1079.08   562.2 1082.05   598.4 1092.54
   610.4 1094.97   622.5 1096.16   634.6 1098.08   743.2 1132.98   755.2 1136.33
   779.3 1139.63   791.4 1143.17   827.3 1157.52   851.7 1166.56  1002.6 1212.94
#Mann= 3 , 0 , 0
       0     0.1       0   494.9   0.045       0   509.9     0.1       0
Bank Sta=   494.9,   509.9
Exp/Cntr=0.3,0.1

Type RM Length L Ch R = 1 ,1659.7,272.64,269.392,267.654
XS GIS Cut Line= 3
     1720253.274      227217.183     1720236.913      227716.957
     1720216.371      228217.969
#Sta/Elev= 30
       0 1147.26    18.2 1144.89    53.8 1138.78    65.7 1135.08   109.8 1128.31
   148.8 1120.24   190.5 1112.89   267.6 1094.53   279.5 1092.48   303.2 1089.36
   338.9 1086.09   386.4 1078.90   454.8 1072.93   492.5 1067.49   505.2 1067.23
   507.5 1067.32   576.5 1071.85   588.4 1074.57   624.0 1086.95   647.8 1093.44
   671.6 1105.24   695.3 1118.56   707.2 1122.72   719.1 1125.13   731.0 1129.60
   819.7 1166.68   869.2 1189.72   885.4 1195.88   956.7 1213.49  1001.5 1220.11
#Mann= 3 , 0 , 0
       0     0.1       0   492.5   0.045       0   507.5     0.1       0
Bank Sta=   492.5,   507.5
Exp/Cntr=0.3,0.1

Type RM Length L Ch R = 1 ,1390.3,392.257,393.44,392.916
XS GIS Cut Line= 3
     1719916.420      227197.620     1719971.589      227695.101
     1719988.864      228200.863
#Sta/Elev= 30
       0 1135.81    14.0 1134.34    61.8 1124.26   145.3 1113.01   158.8 1112.04
   210.0 1111.33   229.1 1109.28   276.8 1100.94   324.6 1088.76   372.4 1075.13
   384.4 1072.83   432.1 1067.04   492.3 1063.64   503.8 1063.45   507.3 1063.52
   569.3 1065.45   618.2 1067.60   634.5 1068.56   646.3 1070.38   658.2 1073.94
   682.0 1084.11   693.9 1088.58   717.6 1093.95   729.5 1097.68   836.4 1139.13
   851.9 1144.43   919.6 1159.79   967.1 1171.39   979.0 1173.63  1005.8 1176.51
#Mann= 3 , 0 , 0
       0     0.1       0   492.3   0.045       0   507.3     0.1       0
Bank Sta=   492.3,   507.3
Exp/Cntr=0.3,0.1

Type RM Length L Ch R = 1 ,996.9,540.551,538.871,538.635
XS GIS Cut Line= 3
     1719596.587      227144.819     1719582.536      227642.372
     1719610.092      228149.990
#Sta/Elev= 30
       0 1153.69   114.3 1128.97   149.9 1119.76   188.6 1108.14   209.3 1102.40
   292.4 1086.98   340.0 1076.52   363.7 1072.03   375.6 1070.43   387.5 1069.54
   439.0 1066.77   475.7 1064.31   513.4 1060.65   518.2 1060.24   528.4 1060.70
   553.8 1064.21   577.6 1065.44   613.3 1066.04   664.2 1065.44   736.8 1067.52
   756.0 1069.96   770.6 1072.35   791.6 1075.97   815.4 1080.99   852.7 1087.30
   874.9 1090.35   903.0 1092.89   958.1 1096.31   984.9 1097.40  1005.6 1097.68
#Mann= 3 , 0 , 0
       0     0.1       0   513.4   0.045       0   528.4     0.1       0
Bank Sta=   513.4,   528.4
Exp/Cntr=0.3,0.1

Type RM Length L Ch R = 1 ,458,177.081,177.017,176.136
XS GIS Cut Line= 3
     1719012.320      227276.881     1719083.350      227787.394
     1719113.628      228284.268
#Sta/Elev= 30
       0 1112.70    42.0 1104.55    52.7 1101.89    77.9 1092.97   101.9 1086.70
   125.9 1082.27   185.8 1074.34   197.8 1073.11   245.7 1071.55   292.3 1068.85
   341.6 1064.80   389.4 1061.56   413.6 1058.60   437.5 1056.60   503.4 1054.92
   509.4 1054.67   518.4 1054.75   583.0 1056.66   627.8 1059.53   640.3 1060.59
   652.2 1062.35   717.8 1075.90   759.3 1085.20   771.2 1088.73   842.5 1118.81
   854.4 1123.14   863.3 1125.23   937.7 1135.63   985.3 1140.76  1013.2 1145.83
#Mann= 3 , 0 , 0
       0     0.1       0   503.4   0.045       0   518.4     0.1       0
Bank Sta=   503.4,   518.4
Exp/Cntr=0.3,0.1

Type RM Length L Ch R = 1 ,281,215.973,221.28,226.851
XS GIS Cut Line= 3
     1718840.821      227323.497     1718912.779      227833.880
     1718943.960      228330.698
#Sta/Elev= 30
       0 1088.86    66.8 1076.41    79.1 1076.07   126.8 1078.92   138.8 1078.65
   174.7 1073.06   186.7 1072.00   246.7 1073.00   282.7 1071.86   378.6 1062.47
   462.5 1057.03   493.1 1053.64   498.5 1053.03   508.1 1053.47   534.3 1055.31
   605.7 1057.42   629.5 1058.93   712.7 1070.93   772.2 1084.33   784.1 1087.92
   800.6 1094.99   828.9 1108.77   855.5 1118.58   867.4 1121.02   879.3 1121.15
   903.1 1118.18   917.7 1118.54   962.5 1133.44   990.9 1140.57  1013.2 1147.24
#Mann= 3 , 0 , 0
       0     0.1       0   493.1   0.045       0   508.1     0.1       0
Bank Sta=   493.1,   508.1
Exp/Cntr=0.3,0.1

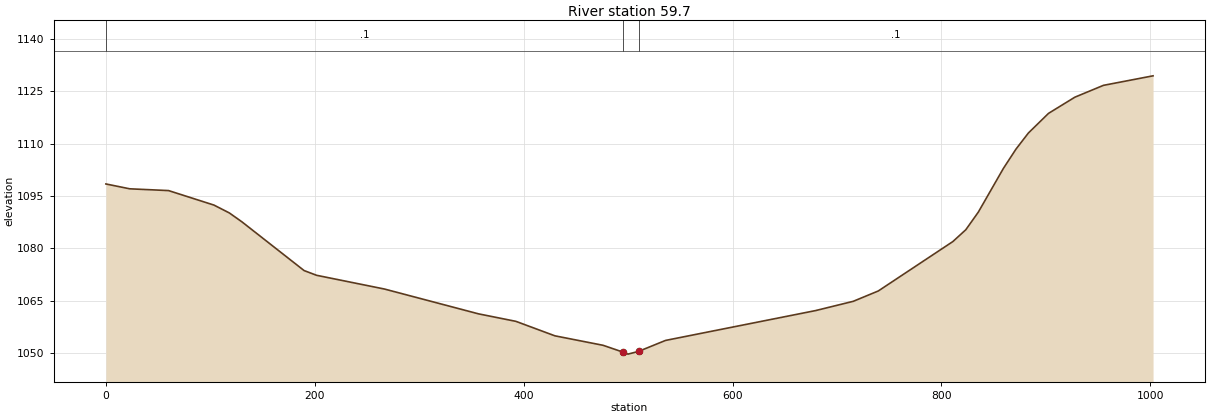
Type RM Length L Ch R = 1 ,59.7,56.972,59.707,61.565
XS GIS Cut Line= 3
     1718740.525      227331.336     1718692.303      227831.634
     1718624.935      228327.203
#Sta/Elev= 30
       0 1098.46    22.8 1097.07    60.0 1096.56   103.5 1092.40   118.2 1090.15
   130.2 1087.61   189.8 1073.62   201.7 1072.27   266.7 1068.33   356.8 1061.21
   392.6 1059.06   429.9 1054.91   476.1 1052.19   495.1 1050.24   499.9 1049.66
   510.1 1050.45   535.9 1053.59   679.6 1062.15   715.6 1064.80   739.6 1067.77
   811.0 1081.94   823.4 1085.33   835.4 1090.39   859.4 1102.92   871.4 1108.43
   883.3 1113.06   902.6 1118.70   927.8 1123.34   955.2 1126.74  1002.7 1129.47
#Mann= 3 , 0 , 0
       0     0.1       0   495.1   0.045       0   510.1     0.1       0
Bank Sta=   495.1,   510.1
Exp/Cntr=0.3,0.1